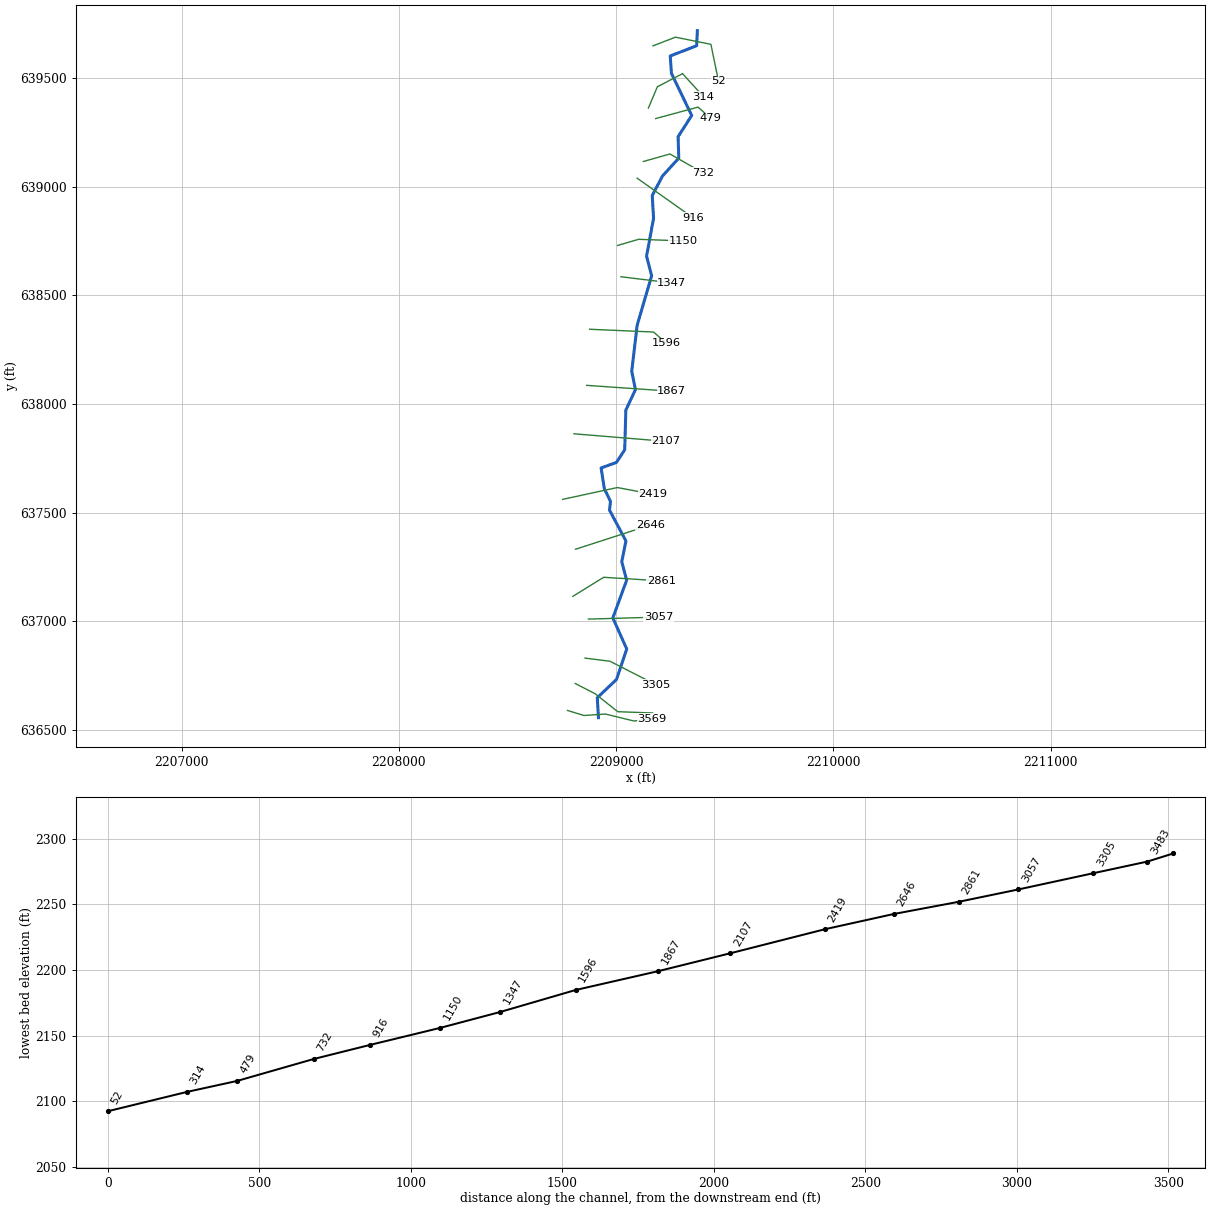
--- LICKRN1.prj (project) ---

Proj Title=LICKRN1
Current Plan=p01
Default Exp/Contr=0,0
English Units
Geom File=g01
Flow File=f01
Plan File=p01
BEGIN DESCRIPTION:
---------- MODELED AS PART OF WVEMD CTP PROGRAM, 2023----------
Stream Name: Lick Run
Flood Zone:  AFH
Upshur County, WV
HEC-RAS Version: RAS 6.3
Vertical Datum: NAVD88
Projection: NAD 1983 StatePlane West Virginia S FIPS 4702 (US Feet)
Terrain: 1-meter LIDAR (FEMA Region III 3DEP collected 2016-2018)
Land Use: 2019 NLCD
Hydrologic Method:
WV 2010 Regional Regression Equations
Additional Model Notes:
US extent goes beyond county boundary
END DESCRIPTION:
DSS Export Rating Curves= 0
DSS Export Rating Curve Sorted= 0
DSS Export Volume Flow Curves= 0
DXF OffsetX= 0
DXF OffsetY= 0
DXF ScaleX= 0
DXF ScaleY= 0

--- LICKRN1.p01 (plan) ---

Plan Title=Floodplain
Program Version=6.31
Short Identifier=Floodplain
Geom File=g01
Flow File=f01
Subcritical Flow
K Sum by GR= 0
Std Step Tol= 0.01
Critical Tol= 0.01
Num of Std Step Trials= 20
Max Error Tol= 0.3
Flow Tol Ratio= 0.001
Split Flow NTrial= 30
Split Flow Tol= 0.02
Split Flow Ratio= 0.02
Log Output Level= 0
Friction Slope Method= 1
Unsteady Friction Slope Method= 2
Unsteady Bridges Friction Slope Method= 1
Parabolic Critical Depth
Global Vel Dist= 0 , 0 , 0
Global Log Level= 0
CheckData=True
Encroach Param=-1 ,0,0, 0
Mapping Interval=1HOUR
Computation Time Step Use Courant=        0
Computation Time Step Use Time Series=    0
Computation Time Step Count To Double=0
Computation Time Step Max Doubling=0
Computation Time Step Max Halving=0
Computation Time Step Residence Courant=0
Run HTab= 0
Run UNet= 0
Run Sediment= 0
Run PostProcess= 0
Run WQNet= 0
Run RASMapper=-1
UNET Theta= 0
UNET Theta Warmup= 0
UNET ZTol= 0
UNET ZSATol= 0
UNET MxIter= 0
UNET Max Iter WO Improvement= 0
UNET MaxInSteps= 0
UNET DtIC= 0
UNET DtMin= 0
UNET MaxCRTS= 0
UNET WFStab= 0
UNET SFStab= 0
UNET WFX= 1
UNET SFX= 1
UNET Gravity=32.17405
UNET 1D Methodology=Finite Difference
UNET DSS MLevel= 1
UNET Pardiso=0
UNET DZMax Abort= 0
UNET Use Existing IB Tables= 0
UNET Froude Reduction=False
UNET Froude Limit= 0
UNET Froude Power= 0
UNET D1 Cores= 0
UNET WindReference=Eulerian
UNET WindDragFormulation=Hsu (1988)
UNET D2 Coriolis=0
UNET D2 Cores= 0
UNET D2 Theta= 1
UNET D2 Theta Warmup= 1
UNET D2 Z Tol= 0.01
UNET D2 Volume Tol= 0.01
UNET D2 Max Iterations= 20
UNET D2 Equation= 0
UNET D2 RampUpFraction=0.1
UNET D2 TimeSlices= 1
UNET D2 Turbulence Formulation=Non-Conservative (original)
UNET D2 Eddy Viscosity=0.3
UNET D2 Transverse Eddy Viscosity=0.1
UNET D2 Smagorinsky Mixing=0
UNET D2 BCVolumeCheck=0
UNET D2 Cores=0
UNET D2 SolverType=PARDISO (Direct)
UNET D2 Minimum Iterations= 3
UNET D2 Maximum Iterations= 30
UNET D2 Restart Number= 10
UNET D2 Relaxation Coeff=1.3
UNET D2 SOR Precondition Iterations= 10
UNET D2 ILUT Maximum Fill= 8
UNET D2 ILUT Tolerance=1E-08
UNET D2 Convergence Tolerance=0.00001
UNET D1D2 MaxIter= 0
UNET D1D2 ZTol=0.01
UNET D1D2 QTol=0.1
UNET D1D2 MinQTol=1
Write IC File= 0
Write IC File at Fixed DateTime=0
Write IC File at Sim End=0
Echo Input=False
Echo Parameters=False
Echo Output=False
Write Detailed= 0
HDF Write Warmup=0
HDF Write Time Slices=0
HDF Flush=0
HDF Compression= 1
HDF Chunk Size= 1
HDF Spatial Parts= 1
HDF Use Max Rows=0
HDF Fixed Rows= 1
Calibration Method= 0
Calibration Iterations= 20
Calibration Max Change=0.05
Calibration Tolerance=0.2
Calibration Maximum=1.5
Calibration Minimum=0.5
Calibration Optimization Method= 1
WQ AD Non Conservative
WQ ULTIMATE=-1
WQ Max Comp Step=1HOUR
WQ Output Interval=15MIN
WQ Output Selected Increments= 0
WQ Create Restart=0
WQ Fixed Restart=0
WQ System Summary=0
WQ Write To DSS=0
Sorting and Armoring Iterations= 10
XS Update Threshold= 0.02
Bed Roughness Predictor= 0
Hydraulics Update Threshold= 0.02
Energy Slope Method= 1
Volume Change Method= 1
Sediment Retention Method= 0
Sediment TS Multiplier= 1
Warm Up Method= 0
XS Weighting Method= 0
Number of US Weighted Cross Sections= 1
Number of DS Weighted Cross Sections= 1
Upstream XS Weight=0
Main XS Weight=1
Downstream XS Weight=0
Number of DS XS's Weighted with US Boundary= 1
Upstream Boundary Weight= 1
Weight of XSs Associated with US Boundary= 0
Number of US XS's Weighted with DS Boundary= 1
Downstream Boundary Weight= 0.5
Weight of XSs Associated with DS Boundary= 0.5
Percentile Method= 0
Sediment Output Level= 3
Mass or Volume Output= 0
Output Increment Type= 1
Profile and TS Output Increment= 1
Transport Output Increment 1
XS Output Flag= 0
XS Output Increment= 10
Read HDF5 Sediment Hotstart= 0
Sediment Hotstart Type= 0
Write Gradation File= 0
Read Gradation Hotstart= 0
Write HDF5 File= 1
Write Binary Output= 1
Write DSS Sediment File= 0
DSS Sediment Output Type= 1
SV Curve= 0
Specific Gage Flag= 0
Subcell Erosion Methods= 0
Subcell Deposition Methods= 0
Advection Scheme= 1
Matrix Solver= 0
Implicit Weighting Factor= 1
Maximum Outer Loop Convergence Iterations= 5
Convergence Maximum Absolute= 0.001
Convergence RMSE= 0.0001
Grain Fractions Max Abs Error= 0.001
Max Subgrid Regions= 1
Max Subgrid Length Scale= 3.402823E+38
Initial Layer Thickness= 3.402823E+38
Min Layer Thickness= 3.402823E+38
Max Layer Thickness= 3.402823E+38
Number of Layers= 5

--- LICKRN1.f01 (steady flow) ---

Flow Title=Flows
Program Version=6.31
Number of Profiles= 1
Profile Names=01pct
River Rch & RM=LICKRN1,Main,3569
     443
Boundary for River Rch & Prof#=LICKRN1,Main            , 1
Up Type= 0
Dn Type= 3
Dn Slope=0.05629
DSS Import GetInterval= 0
DSS Import GetPeak= 0
DSS Import FillOption= 0

--- LICKRN1.g01 (geometry) ---

Geom Title=Geometry
Program Version=6.31

River Reach=LICKRN1         ,Main
Reach XY= 30
      2208918.52      636555.803     2208912.997      636647.661
     2209001.393      636731.536      2209048.61      636871.556
     2208984.652      637015.039     2209048.238       637188.74
      2209025.66      637273.616     2209044.918      637368.995
     2208969.428      637510.818     2208973.749      637551.109
     2208945.677      637609.744      2208930.51      637705.066
      2209001.25      637730.506     2209039.252      637788.912
     2209044.489      637971.227      2209088.73      638065.775
     2209071.503      638149.593     2209096.428      638361.583
      2209163.19      638589.455     2209139.896      638679.511
     2209172.032      638854.443     2209165.908      638959.036
     2209213.412      639049.006       2209288.1      639130.992
     2209284.924      639229.489     2209347.623      639327.271
      2209254.39      639520.661     2209248.839      639601.102
     2209370.344      639648.176     2209373.578      639717.427

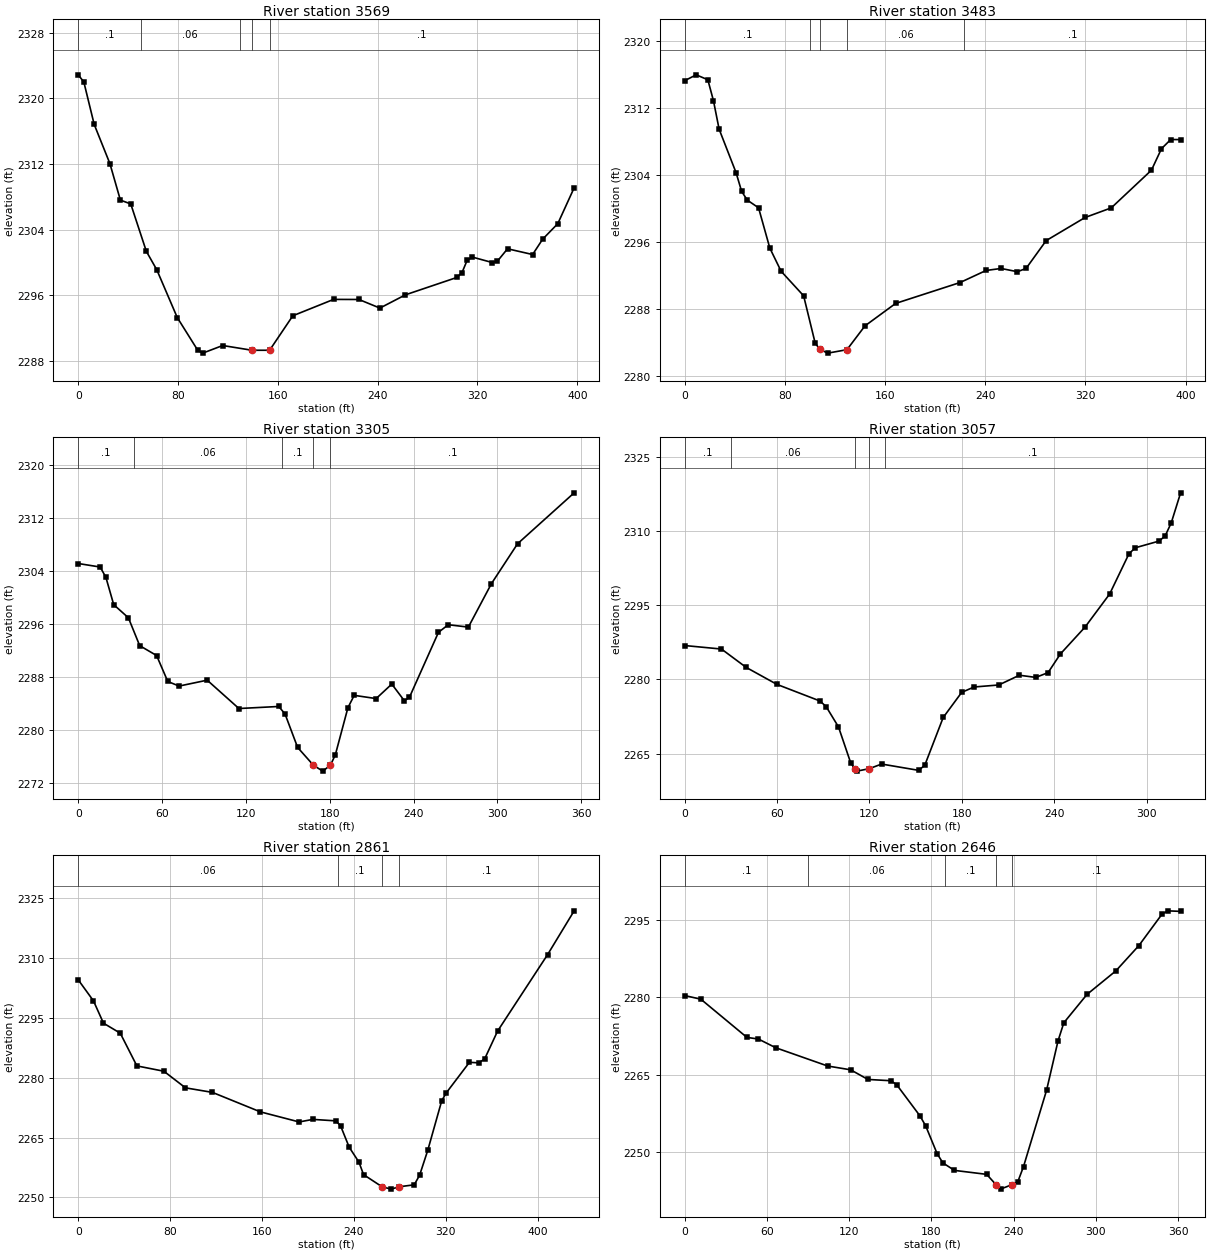
Type RM Length L Ch R = 1 ,3569    ,86.3,86.2,86.3
XS GIS Cut Line= 5
2208775.89191013636589.066153493  2208851.802028636565.857926513
2208950.42359681636572.496636767 2209082.5908718636540.455074527
2209165.13865614   636551.143206
#Sta/Elev= 30
       0 2322.89     4.5 2322.02    12.8 2316.84    25.4 2312.05    33.8 2307.59
    42.1 2307.13    54.6 2301.34      63 2299.08    79.4 2293.25    95.8 2289.26
    99.8 2288.91   115.8 2289.84   139.3 2289.26   153.42289.259     172 2293.47
   204.7 2295.47     225 2295.46   241.8 2294.41   262.3 2296.03   303.5 2298.15
   307.6 2298.74   311.7 2300.23   315.8 2300.64   331.9 2299.97     336 2300.14
   344.1 2301.65   364.2 2300.95   372.3 2302.83   384.4 2304.72   397.5  2309.1
#Mann= 5 ,-1,0
       0      .1       0      50     .06       0  129.38      .1       0
139.2792    .045       0153.3692      .1       0
Bank Sta=139.3,153.4
XS Rating Curve= 0 ,0
Exp/Cntr(USF)=0,0
Exp/Cntr=0.3,0.1

Type RM Length L Ch R = 1 ,3483    ,175.2,178,179.3
XS GIS Cut Line= 4
2208811.70264349636713.0390052792208903.41747096636665.812713524
2209007.33150288636583.3304069492209167.51974546636577.499762705
#Sta/Elev= 30
       0 2315.29     9.2 2315.99    18.5  2315.4      23 2312.88    27.5 2309.49
      41  2304.3    45.5 2302.04      50    2301      59 2300.08      68 2295.26
      77 2292.49      95 2289.55   104.2  2283.9     1082283.127   114.3 2282.69
   129.62283.101     144 2285.95   168.5 2288.64     220 2291.14   240.7 2292.58
   252.7 2292.82   265.8 2292.43   272.7 2292.83   288.7 2296.15   319.8 2298.92
   340.7 2300.07   372.8 2304.58   380.8 2307.15   388.2 2308.25   396.1 2308.24
#Mann= 5 ,-1,0
       0      .1       0     100     .06       0  108.03    .045       0
   129.6     .06       0  223.16      .1       0
Bank Sta=108,129.6
XS Rating Curve= 0 ,0
Exp/Cntr(USF)=0,0
Exp/Cntr=0.3,0.1

Type RM Length L Ch R = 1 ,3305    ,240.8,247.9,252.2
XS GIS Cut Line= 3
2208856.55494065636829.9177373672208971.54069449636815.544518137
2209184.40122689636706.718715397
#Sta/Elev= 30
       0 2305.18    15.7 2304.65    19.8  2303.1    25.4 2298.97    35.9 2296.99
      44 2292.78    56.1 2291.29    64.1 2287.37    72.2 2286.68    92.3 2287.57
     115 2283.29   143.5  2283.6     148 2282.47     157 2277.42  168.36 2274.72
     175 2273.84   180.5 2274.74     184  2276.3     193 2283.41   197.5 2285.28
   213.2 2284.79   224.4 2286.98   233.4 2284.46     237 2284.97   257.8 2294.79
   264.8 2295.94   279.2 2295.58   295.7 2302.14   314.4 2308.16   354.9 2315.85
#Mann= 5 ,-1,0
       0      .1       0      40     .06       0  145.88      .1       0
  168.36    .045       0   180.5      .1       0
Bank Sta=168.36,180.5
XS Rating Curve= 0 ,0
Exp/Cntr(USF)=0,0
Exp/Cntr=0.3,0.1

Type RM Length L Ch R = 1 ,3057    ,194.7,195.8,194.1
XS GIS Cut Line= 2
2208872.30973008637009.4805883342209194.24956116  637018.7754391
#Sta/Elev= 30
       0 2286.83    23.9 2286.12    39.9 2282.42    59.9 2278.98    87.9 2275.62
    91.9 2274.48    99.9 2270.38   107.9 2263.05  110.672261.942   111.9 2261.45
   119.9 2261.95   127.9 2262.88   151.9 2261.61   155.9 2262.61   167.9 2272.29
   179.9 2277.36   187.9 2278.45     204 2278.86   217.4 2280.83     228 2280.39
     236 2281.35     244 2285.12     260 2290.55     276 2297.24   288.6  2305.4
   292.7 2306.59     308 2307.93     312 2308.95     316 2311.61   322.1 2317.69
#Mann= 5 ,-1,0
       0      .1       0      30     .06       0  110.67    .045       0
   119.9     .06       0     130      .1       0
Bank Sta=110.67,119.9
XS Rating Curve= 0 ,0
Exp/Cntr(USF)=0,0
Exp/Cntr=0.3,0.1

Type RM Length L Ch R = 1 ,2861    ,211.4,215.7,219.6
XS GIS Cut Line= 3
2208800.79046989637114.2133146552208942.39698074637201.907839991
2209207.25725217 637185.52683398
#Sta/Elev= 30
       0  2304.5    13.3 2299.22      22 2293.64    36.6 2291.14    51.1 2282.94
    74.6 2281.61    93.4 2277.45   116.9 2276.31   158.6 2271.44   192.4 2268.91
   204.4 2269.55   224.4 2269.18   228.5 2267.93     236 2262.58   244.5 2258.84
   248.5 2255.72   264.5  2252.7   272.5 2252.09  279.622252.686   292.6 2253.17
   297.3 2255.56   304.4  2261.8   316.6 2274.24   320.6 2276.22   340.7 2283.84
   348.7 2283.71   353.9 2284.66   365.2 2291.65   408.8 2310.82   431.9 2321.77
#Mann= 4 ,-1,0
       0     .06       0  226.56      .1       0   264.5    .045       0
  279.62      .1       0
Bank Sta=264.5,279.62
XS Rating Curve= 0 ,0
Exp/Cntr(USF)=0,0
Exp/Cntr=0.3,0.1

Type RM Length L Ch R = 1 ,2646    ,227.2,226.7,224.4
XS GIS Cut Line= 2
2208812.93660756637331.0459688832209157.19033963637442.319902482
#Sta/Elev= 30
       0 2280.35    11.8 2279.64    45.4 2272.22    53.8  2271.9    66.5  2270.2
   104.3 2266.66   121.1 2265.92   133.7 2264.05   150.5  2263.8   154.7 2263.01
   171.6 2256.99   175.8 2255.04   184.2 2249.61   188.4 2247.83   196.8 2246.38
   220.3 2245.61  227.132243.609   230.4 2242.74   238.8 2243.61     243 2244.15
   247.2 2247.13     264 2261.94   272.4 2271.57   276.6 2275.06   293.5 2280.57
   314.5 2285.13   331.3 2290.04   348.1 2296.12   352.3 2296.81   361.8  2296.7
#Mann= 5 ,-1,0
       0      .1       0      90     .06       0     190      .1       0
  227.13    .045       0   238.8      .1       0
Bank Sta=227.13,238.8
XS Rating Curve= 0 ,0
Exp/Cntr(USF)=0,0
Exp/Cntr=0.3,0.1

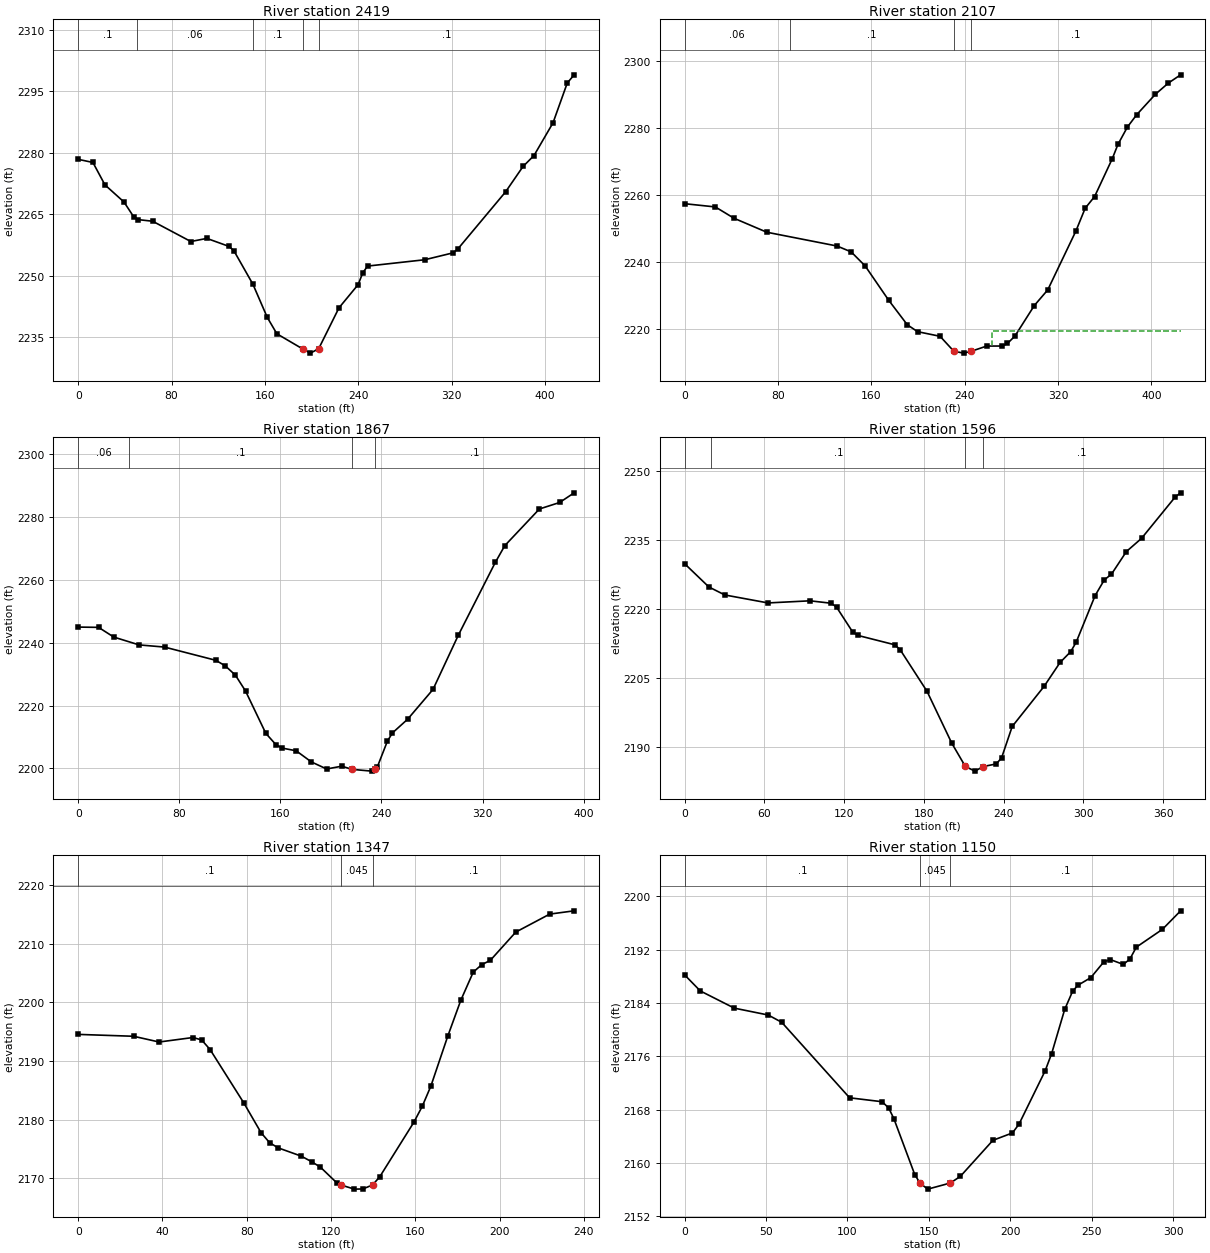
Type RM Length L Ch R = 1 ,2419    ,312.1,312.1,306.2
XS GIS Cut Line= 3
2208753.82233034 637560.548456932209005.34778441637615.026320254
2209169.94047786 637583.73052643
#Sta/Elev= 30
       0 2278.37    12.6 2277.61    22.9 2272.15    39.2 2267.98    47.4 2264.43
    51.5 2263.68    63.8 2263.29    96.5 2258.35   110.2 2259.11   129.3 2257.15
   133.4 2256.09   149.7 2247.93     162 2239.85   170.2 2235.87  192.182232.205
   198.9 2231.16     206 2232.22   223.4 2242.19   239.8 2247.84   243.9 2250.79
     248 2252.37   296.9 2253.91   321.3  2255.6   325.4 2256.59   366.1 2270.43
   381.1 2276.63   390.5  2279.3   406.8 2287.27     419 2296.97   424.9 2298.96
#Mann= 5 ,-1,0
       0      .1       0      50     .06       0     150      .1       0
  192.18    .045       0     206      .1       0
Bank Sta=192.18,206
XS Rating Curve= 0 ,0
Exp/Cntr(USF)=0,0
Exp/Cntr=0.3,0.1

Type RM Length L Ch R = 1 ,2107    ,238.5,239.3,239.4
XS GIS Cut Line= 2
 2208805.9851667637862.2444885732209229.70188144637827.471384324
#Sta/Elev= 30
       0 2257.49    26.3 2256.52    42.3 2253.14    70.4 2248.97   130.6 2244.85
   142.7  2243.1   154.7  2238.9   174.8 2228.69   190.8 2221.34   199.6 2219.27
   218.9 2217.89  230.622213.455     239 2212.86  245.72 2213.43   258.9 2214.97
   272.3 2214.98   276.7 2215.76   283.1 2217.96   299.7 2227.08   311.2 2231.74
   335.3  2249.3   343.3 2256.14   351.4 2259.64   366.5 2270.92   371.4 2275.21
   379.5 2280.39   387.5 2284.09   403.5 2290.18   414.7 2293.55   425.1 2295.98
#Mann= 4 ,-1,0
       0     .06       0      90      .1       0  230.62    .045       0
  245.72      .1       0
#XS Ineff= 2 , 0
                          263.42         2219.45
Permanent Ineff=
       F       F
Bank Sta=230.62,245.72
XS Rating Curve= 0 ,0
Exp/Cntr(USF)=0,0
Exp/Cntr=0.3,0.1

Type RM Length L Ch R = 1 ,1867    ,270.6,271.8,271.1
XS GIS Cut Line= 2
2208864.06912972638085.1787235952209255.58852571638058.132975845
#Sta/Elev= 30
       0 2244.91    16.1 2244.82    28.2 2241.73    48.2 2239.25    68.3 2238.56
   108.9 2234.36   116.4 2232.59   124.4 2229.64   132.4 2224.62   148.5 2211.14
   156.5 2207.56   161.4 2206.48   172.5 2205.62   184.5 2202.09   196.6 2199.84
   208.6 2200.73   216.6 2199.73   232.2 2199.16  234.612199.774   236.7 2200.46
   244.7 2208.68   248.7  2211.3   260.7 2215.64   280.8 2225.11   300.8 2242.31
   330.1 2265.45   337.6 2270.77     365 2282.42     381 2284.48   392.5 2287.55
#Mann= 4 ,-1,0
       0     .06       0      40      .1       0   216.6    .045       0
  234.61      .1       0
Bank Sta=216.6,234.61
XS Rating Curve= 0 ,0
Exp/Cntr(USF)=0,0
Exp/Cntr=0.3,0.1

Type RM Length L Ch R = 1 ,1596    ,247.7,248.6,246.6
XS GIS Cut Line= 3
2208878.00662556638343.4628179862209172.46479535638330.520322644
2209231.09186752638278.573295773
#Sta/Elev= 30
       0  2229.9    18.2 2224.86    30.2 2223.12    62.7 2221.39    94.3 2221.85
   110.3 2221.32   114.3 2220.46   126.3 2215.11   130.3 2214.33   158.3 2212.28
   162.3 2211.14   182.3  2202.2   200.9 2190.94  211.162185.859   218.4 2184.85
  224.572185.848   234.4 2186.41   238.4 2187.73   246.4 2194.55   270.4 2203.27
   282.4 2208.45   290.4  2210.8   294.5 2212.84   308.8    2223   315.7  2226.4
   321.1 2227.64   332.3 2232.55   343.7 2235.42   369.1 2244.43   373.1 2245.31
#Mann= 4 ,-1,0
       0     .06       0      20      .1       0  211.16    .045       0
  224.57      .1       0
Bank Sta=211.16,224.57
XS Rating Curve= 0 ,0
Exp/Cntr(USF)=0,0
Exp/Cntr=0.3,0.1

Type RM Length L Ch R = 1 ,1347    ,195,197.3,197.1
XS GIS Cut Line= 2
2209022.04802671638585.0637775932209255.72450862638556.473168433
#Sta/Elev= 30
       0 2194.55    26.3 2194.23    38.4 2193.25    54.5 2194.02    58.6  2193.6
    62.6 2191.96    78.7 2182.79    86.8 2177.76    90.8 2176.08    94.8 2175.19
   105.9 2173.76   110.9 2172.79     115 2171.87     123 2169.11  124.652168.841
   131.1 2168.13   135.1 2168.16  139.772168.848   143.2 2170.28   159.3 2179.54
   163.3 2182.27   167.4 2185.73   175.4 2194.24   181.6 2200.38   187.5 2205.18
   191.5 2206.45   195.6 2207.19   207.7 2212.02   223.8 2215.09   235.4 2215.65
#Mann= 3 ,-1,0
       0      .1       0  124.65    .045       0  139.77      .1       0
Bank Sta=124.65,139.77
XS Rating Curve= 0 ,0
Exp/Cntr(USF)=0,0
Exp/Cntr=0.3,0.1

Type RM Length L Ch R = 1 ,1150    ,239.4,233.4,225.6
XS GIS Cut Line= 3
2209006.92294771638729.2259503442209103.62695063638757.392164787
2209307.36256843638749.881174269
#Sta/Elev= 30
       0 2188.19     9.6 2185.79    30.5 2183.21    51.3 2182.18    59.6 2181.09
   101.3 2169.76   121.3 2169.17   125.3 2168.23   128.5 2166.62   141.3 2158.25
  144.572156.942   149.3 2156.06   163.2 2156.98   169.3 2157.97   189.3 2163.38
   201.3 2164.49   205.3 2165.79   221.4 2173.81   225.4  2176.4   233.4 2183.02
   238.2 2185.71   241.4 2186.63   249.4 2187.78   257.4 2190.14   261.4  2190.5
   269.4 2189.77   273.4 2190.56   277.4 2192.36   293.4 2195.03   304.6 2197.81
#Mann= 3 ,-1,0
       0      .1       0  144.57    .045       0   163.2      .1       0
Bank Sta=144.57,163.2
XS Rating Curve= 0 ,0
Exp/Cntr(USF)=0,0
Exp/Cntr=0.3,0.1

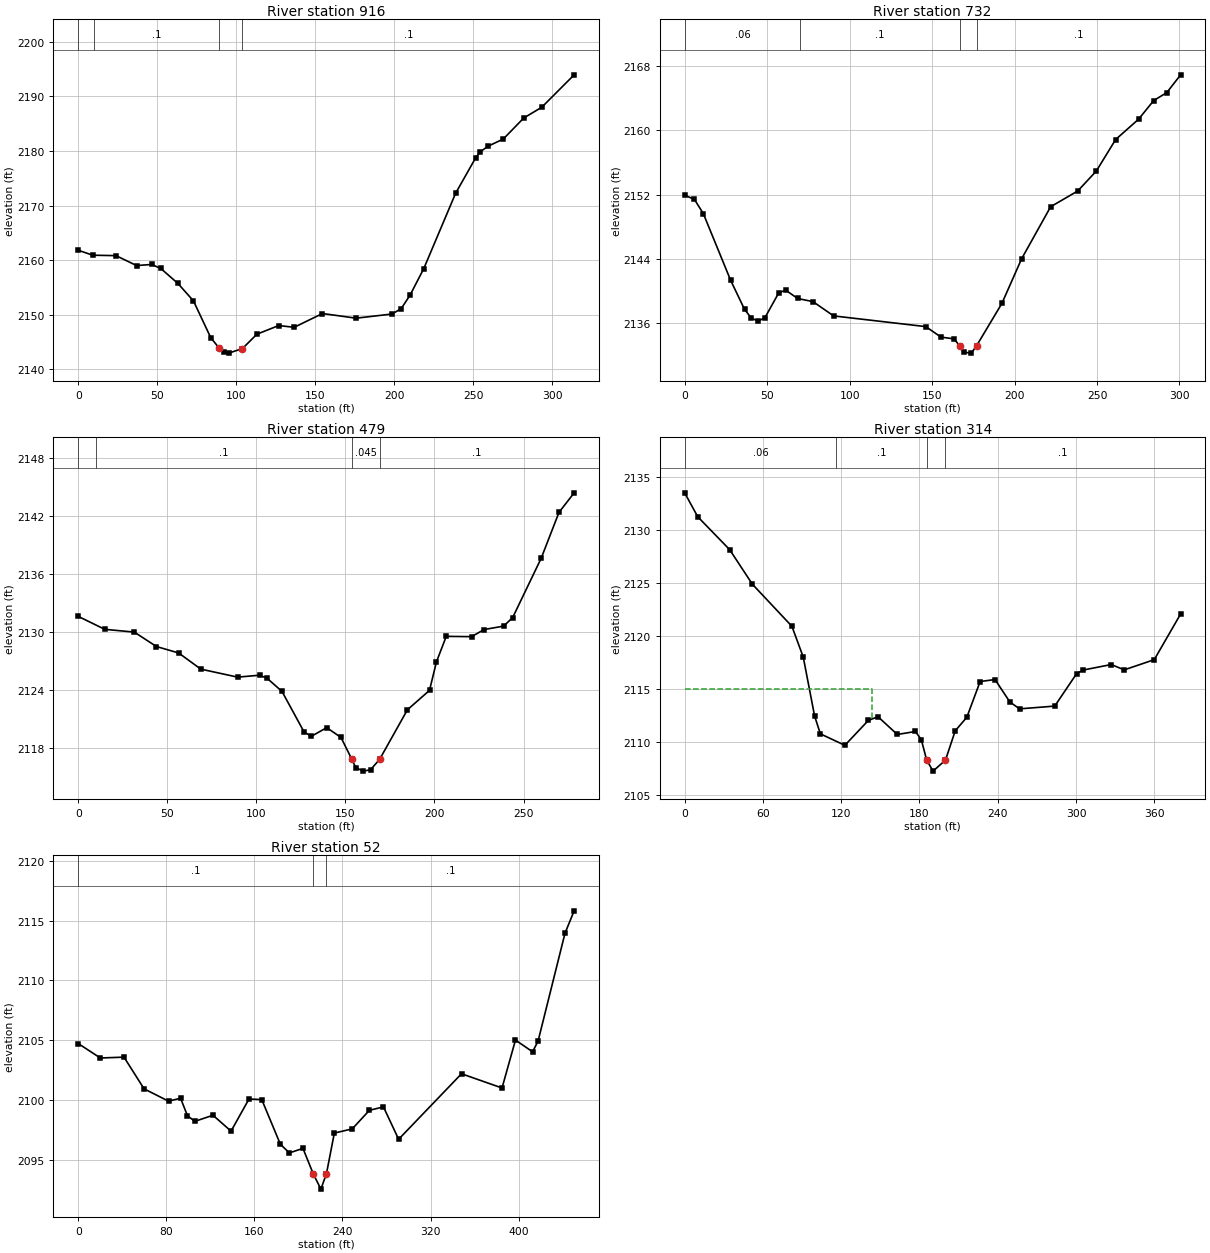
Type RM Length L Ch R = 1 ,916     ,183.5,184.7,185.4
XS GIS Cut Line= 2
2209096.69891651639038.4759555642209352.68747546638857.216975937
#Sta/Elev= 30
       0 2161.82     9.2 2160.91    23.9 2160.83    36.9 2159.02    46.5 2159.21
    52.2 2158.49    63.1 2155.73    72.9 2152.54    83.8 2145.83   89.162143.891
    92.2 2143.13    95.2 2142.98   103.9 2143.82     113 2146.44   126.8 2148.03
   136.6 2147.71   154.5 2150.23   175.8 2149.38   198.5 2150.14   204.3 2151.13
   209.9 2153.59   218.6 2158.47   238.7 2172.24   251.4 2178.74   254.2 2179.81
   259.1 2180.85   268.9 2182.19   281.8 2186.03   293.2    2188   313.7 2193.94
#Mann= 4 ,-1,0
       0     .06       0      10      .1       0   89.16    .045       0
   103.9      .1       0
Bank Sta=89.16,103.9
XS Rating Curve= 0 ,0
Exp/Cntr(USF)=0,0
Exp/Cntr=0.3,0.1

Type RM Length L Ch R = 1 ,732     ,240.5,252.9,259.8
XS GIS Cut Line= 3
2209125.28658314639115.5882776982209247.33284976639150.049826034
2209398.39367294639063.855921292
#Sta/Elev= 30
       0 2151.92     5.9  2151.4    11.3 2149.64    27.9 2141.34    36.3 2137.75
    40.4 2136.67    44.6 2136.29    48.7 2136.73      57 2139.79    61.2 2140.14
    68.5  2139.1    77.8 2138.71    90.3 2136.94   146.2 2135.61   155.4 2134.31
   163.3 2134.09  166.66 2133.25   169.2 2132.43   173.8 2132.32     177 2133.24
   192.3 2138.48   204.3 2144.03   221.9 2150.49   238.3 2152.44   249.6 2154.92
   261.3 2158.83   275.2 2161.35   284.4 2163.67   292.3 2164.65   300.7 2166.86
#Mann= 4 ,-1,0
       0     .06       0      70      .1       0  166.66    .045       0
     177      .1       0
Bank Sta=166.66,177
XS Rating Curve= 0 ,0
Exp/Cntr(USF)=0,0
Exp/Cntr=0.3,0.1

Type RM Length L Ch R = 1 ,479     ,161,164.8,166.7
XS GIS Cut Line= 3
2209181.77168971639313.0009799632209376.67008956639365.713158227
2209434.04905055639315.056202394
#Sta/Elev= 30
       0 2131.63    14.9 2130.29    31.5    2130    43.9 2128.51    56.4 2127.84
    68.8 2126.17    89.5 2125.34   101.9 2125.54   106.1 2125.21   114.4 2123.86
   126.8 2119.66   130.9 2119.22   139.5 2120.11   147.5  2119.1   153.62116.838
   155.8 2115.97     160 2115.61   164.1 2115.75   169.2 2116.83   184.8 2121.96
   197.2 2123.97   201.1 2126.92   206.6 2129.56   220.8 2129.53   227.9 2130.27
   238.8 2130.62   243.9 2131.51   259.9 2137.65   269.9  2142.4   278.4 2144.42
#Mann= 4 ,-1,0
       0     .06       0      10      .1       0   153.6    .045       0
   169.2      .1       0
Bank Sta=153.6,169.2
XS Rating Curve= 0 ,0
Exp/Cntr(USF)=0,0
Exp/Cntr=0.3,0.1

Type RM Length L Ch R = 1 ,314     ,262.1,262.1,262.1
XS GIS Cut Line= 4
2209148.28647821639361.3685076852209189.49904621639459.248356684
2209305.40939371639519.7793159332209401.78240819639413.850137247
#Sta/Elev= 30
       0 2133.47      10 2131.22    34.5 2128.12    51.9 2124.87    82.2 2120.91
    90.9 2118.01    99.6 2112.47     104 2110.79   122.8 2109.71   140.8 2112.05
   148.2  2112.4     163 2110.73   176.9 2111.01   181.4 2110.24  185.512108.325
   190.4 2107.28  199.942108.318   207.4 2111.07   216.3 2112.35   226.5 2115.71
   237.9  2115.9   249.3 2113.79   256.7 2113.14   283.7  2113.4   300.5 2116.46
   305.4 2116.79     327 2117.31     337 2116.81     360 2117.77   380.2 2122.07
#Mann= 4 ,-1,0
       0     .06       0   116.2      .1       0  185.51    .045       0
  199.94      .1       0
#XS Ineff= 2 , 0
          143.89 2115.05
Permanent Ineff=
       F       F
Bank Sta=185.51,199.94
XS Rating Curve= 0 ,0
Exp/Cntr(USF)=0,0
Exp/Cntr=0.3,0.1

Type RM Length L Ch R = 1 ,52      ,,,
XS GIS Cut Line= 4
2209169.41231247639647.6547484852209272.84591781639687.588093548
2209435.89000073639654.6313449872209470.98400933639485.010303398
#Sta/Elev= 30
       0 2104.71    20.1  2103.5    41.6 2103.57    59.8 2100.92      82 2099.89
      93 2100.13    99.2 2098.67   105.9  2098.2   122.4 2098.71   138.8 2097.38
   155.1 2100.07   166.7 2100.02   183.6 2096.28   191.8 2095.56   204.1 2095.94
  213.58 2093.78   220.4 2092.53  225.482093.835   232.6 2097.22   248.9 2097.57
   264.4 2099.12   277.2 2099.41     291  2096.7   348.1 2102.18   384.9 2100.99
   397.1    2105   412.6 2104.02   417.6  2104.9   442.1 2113.94   450.4 2115.81
#Mann= 3 ,-1,0
       0      .1       0  213.58    .045       0  225.48      .1       0
Bank Sta=213.58,225.48
XS Rating Curve= 0 ,0
Exp/Cntr(USF)=0,0
Exp/Cntr=0.3,0.1
LCMann Table=0

Chan Stop Cuts=-1
Use User Specified Reach Order=0
Composite Channel Slope=5